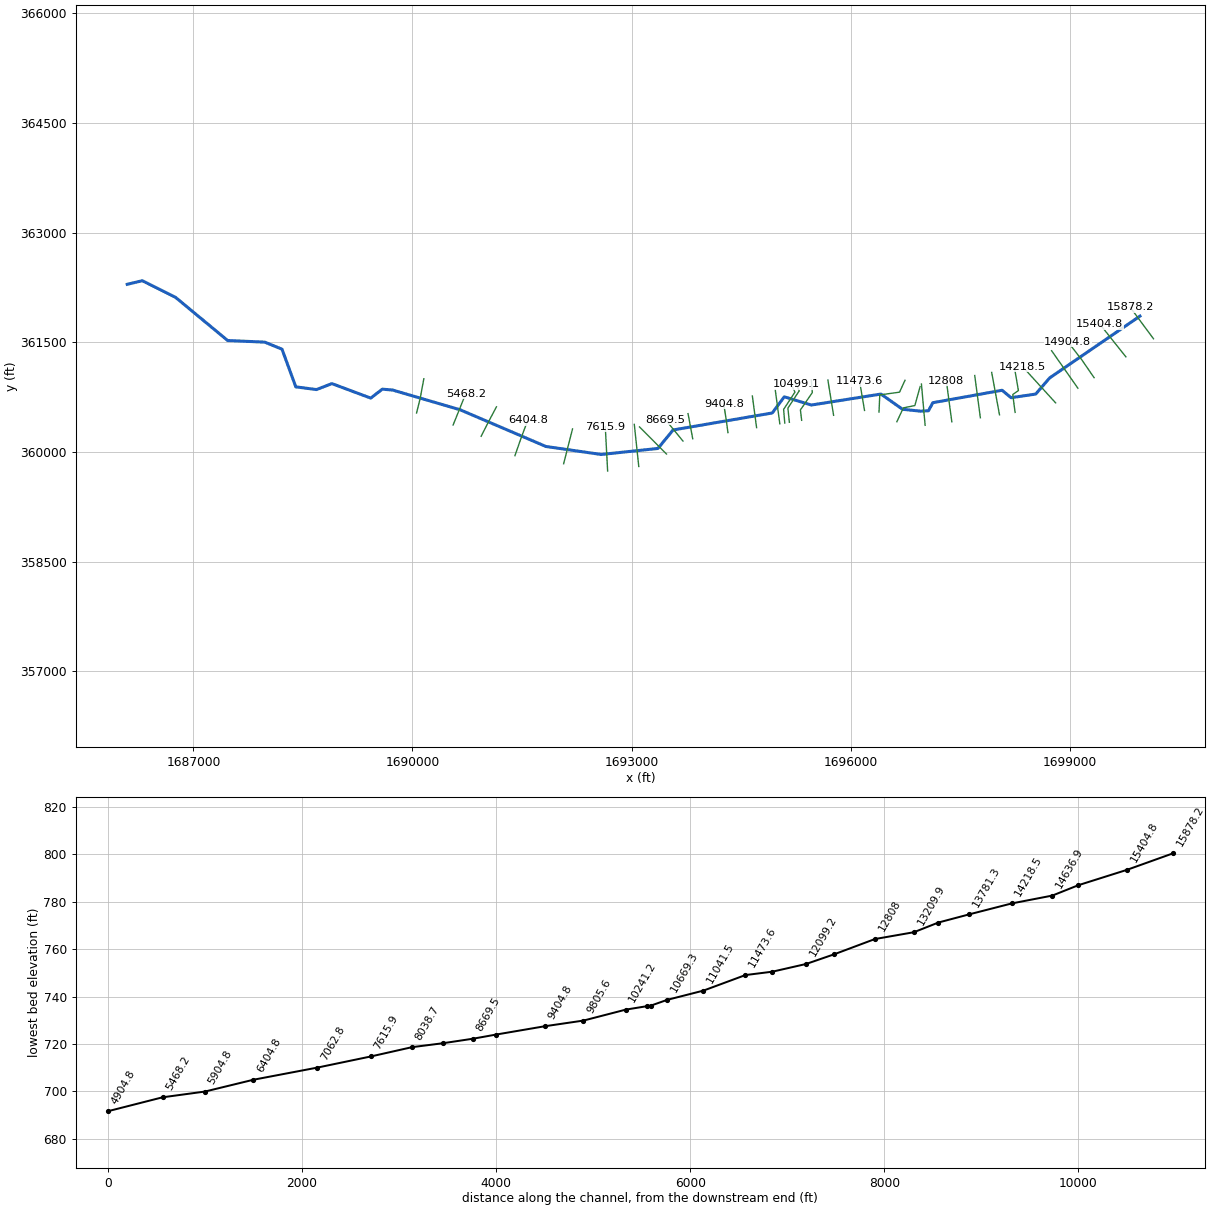
--- TRACEFK.prj (project) ---

Proj Title=TRACEFK
Current Plan=p01
Default Exp/Contr=0,0
English Units
Geom File=g01
Flow File=f01
Plan File=p01
BEGIN DESCRIPTION:
END DESCRIPTION:
DSS Export Rating Curves= 0
DSS Export Rating Curve Sorted= 0
DSS Export Volume Flow Curves= 0
DXF OffsetX= 0
DXF OffsetY= 0
DXF ScaleX= 0
DXF ScaleY= 0

--- TRACEFK.p01 (plan) ---

Plan Title=Floodplain
Program Version=4.00
Geom File=g01
Flow File=f01
K Sum by GR=0
Std Step Tol=0.01
Critical Tol=0.01
Num of Std Step Trials=20
Max Error Tol=0.3
Flow Tol Ratio=0.001
Split Flow NTrial=30
Split Flow Tol=0.02
Split Flow Ratio=0.02
Log Output Level=0
Friction Slope Method=1
Unsteady Friction Slope Method=2
Unsteady Bridges Friction Slope Method=1
Global Log Level=0
CheckData=False
Run HTab=0
Run UNet=0
Run PostProcess=0
UNET Theta=0
UNET Theta Warmup=0
UNET ZTol=0
UNET ZSATol=0
UNET MxIter=0
UNET MaxInSteps=0
UNET DtIC=0
UNET DtMin=0
UNET MaxCRTS=0
UNET WFStab=0
UNET SFStab=0
UNET WFX=0
UNET SFX=0
UNET DSS MLevel=0
UNET DZMax Abort=0
UNET Convert EG Bridges=0
UNET Use Existing IB Tables=0
UNET Froude Limit=0
UNET Froude Power=0
Write IC File=0
Echo Input=False
Echo Output=False
Write Detailed=0

--- TRACEFK.f01 (steady flow) ---

Flow Title=NFF Regression Equation
Program Version=4.10
Number of Profiles= 1
Profile Names=P100yr
River Rch & RM=TRACEFK,Main            ,15878.2
688.9831
River Rch & RM=TRACEFK,Main            ,15404.8
1055.714
River Rch & RM=TRACEFK,Main            ,12808
1100.138
River Rch & RM=TRACEFK,Main            ,12099.2
1222.293
River Rch & RM=TRACEFK,Main            ,9404.8
1354.877
River Rch & RM=TRACEFK,Main            ,7062.8
1505.189
River Rch & RM=TRACEFK,Main            ,5468.2
1562.038
River Rch & RM=TRACEFK,Main            ,4904.8
1771.225
River Rch & RM=TRACEFK,Main            ,4477.3
1816.579
River Rch & RM=TRACEFK,Main            ,69.2
2006.328
Boundary for River Rch & Prof#=TRACEFK,Main            , 1
Up Type= 0
Dn Type= 3
Dn Slope=0.003366
DSS Import GetInterval= 0
DSS Import GetPeak= 0
DSS Import FillOption= 0

--- TRACEFK.g01 (geometry) ---

Geom Title=USGS 10m DEM
Program Version=4.10

River Reach=TRACEFK         ,Main
Reach XY= 30
     1699961.188      361858.287     1698724.062      361012.238
       1698533.8      360791.808     1698196.779      360741.961
     1698072.484      360843.598     1697124.409      360673.339
     1697065.498      360563.286     1696953.504      360558.107
     1696710.351      360583.355     1696414.309      360791.808
     1695461.249      360641.618     1695090.564      360754.261
     1694926.132       360532.86     1693568.272      360300.454
     1693360.725      360047.397     1692583.362       359965.18
      1691826.91      360074.586     1690652.125      360576.752
     1689728.392      360846.576     1689587.265      360858.876
     1689427.883      360736.523     1688896.756       360934.75
     1688684.951      360853.153     1688402.052      360890.479
     1688213.249       361405.67     1687978.007      361502.024
     1687469.087      361524.485      1686755.09      362115.306
     1686301.379      362342.845     1686093.965      362293.428

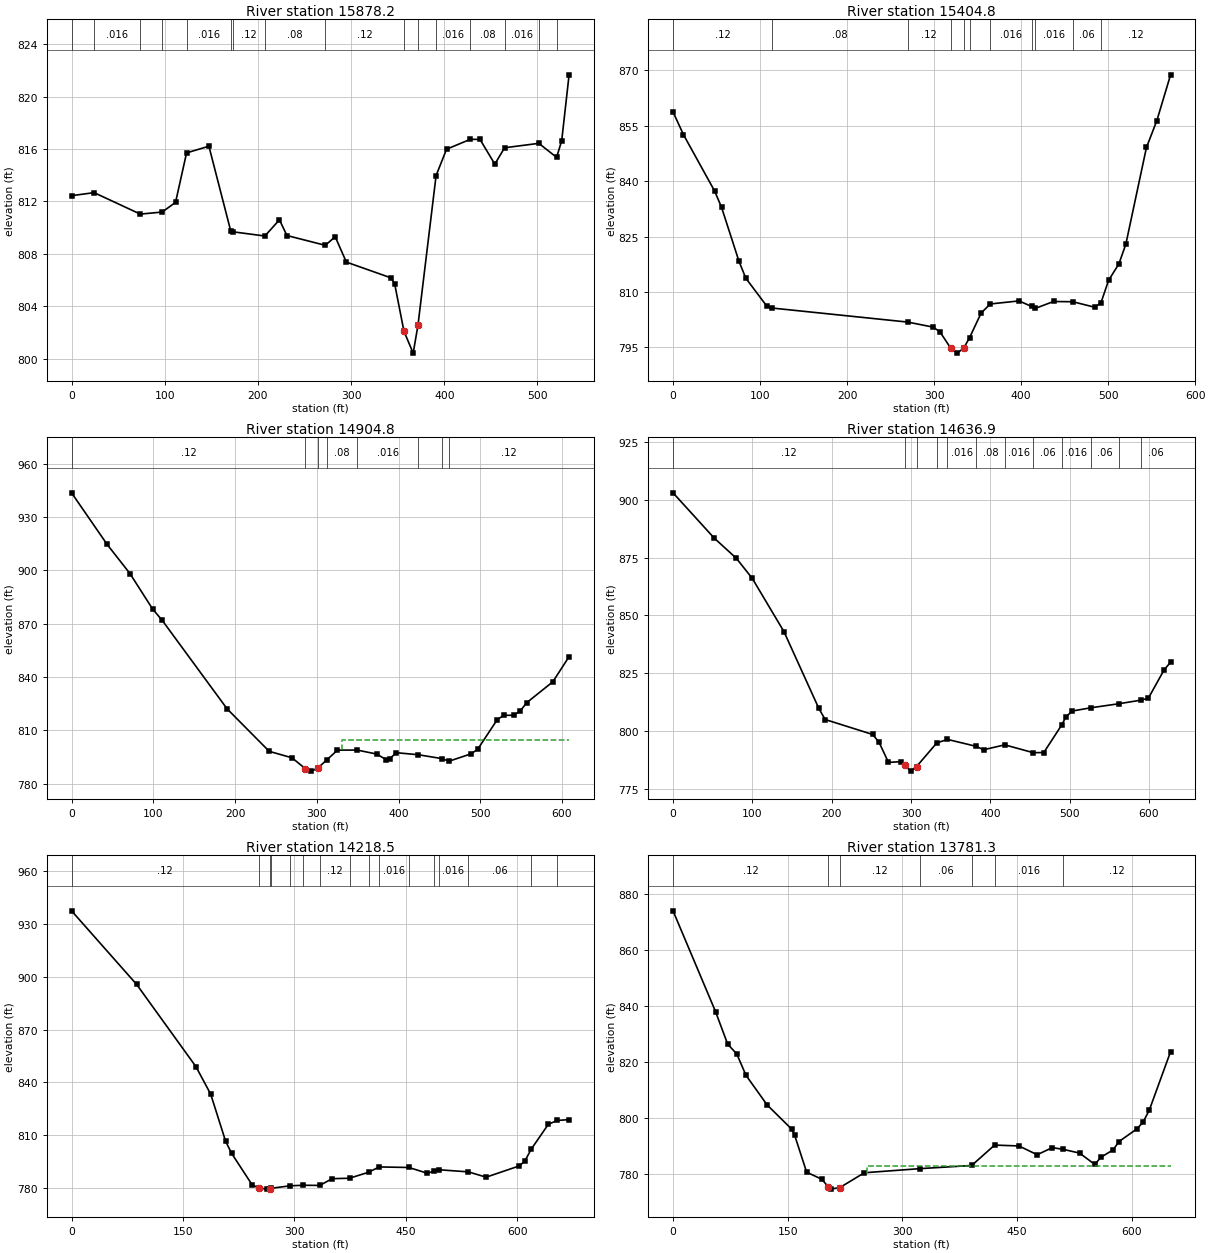
Type RM Length L Ch R = 1 ,15878.2 ,472.5,473.4,473.4
XS GIS Cut Line= 2
     1700145.925      361548.581      1699828.25      361977.738
#Sta/Elev= 30
       0  812.44   24.15 812.675   73.79811.0352   97.21811.1923   111.6  811.93
  123.42815.7086   147.4  816.22   170.7809.7815  173.06809.6848  207.45809.3625
   223.1   810.6   231.1   809.4  272.34808.6516   282.9  809.31   294.9  807.37
   342.7  806.17   346.7  805.72   356.7  802.09   366.6  800.42   371.7  802.53
  391.19813.9788   402.4  815.99  427.94816.7461   438.3  816.74   454.2  814.85
  464.68816.1006  501.43816.4384  520.53815.3665     526  816.65   533.9  821.67
#Mann= 16 ,-1 , 0
       0     .12       0   24.15    .016       0   73.79     .12       0
   97.21     .08       0  123.42    .016       0   170.7     .06       0
  173.06     .12       0  207.45     .08       0  272.34     .12       0
   356.7    .045       0   371.7     .08       0  391.19    .016       0
  427.94     .08       0  464.68    .016       0  501.43     .06       0
  520.53     .12       0
Bank Sta=356.7,371.7
XS Rating Curve= 0 ,0
Exp/Cntr=0.3,0.1

Type RM Length L Ch R = 1 ,15404.8 ,501,500,499.2
XS GIS Cut Line= 3
     1699768.103      361301.084     1699564.639      361556.496
     1699411.836      361748.312
#Sta/Elev= 30
       0   858.7      12  852.54    47.8   837.3    55.8  832.87    75.7  818.37
    83.6  813.75   107.5  806.26  114.26805.6517  269.91801.8589   298.7  800.51
   306.6  799.28     319  794.86   326.6  793.47     334  794.78  340.83797.6732
   354.2  804.35  364.71806.7646   397.7  807.59  412.11806.0796  416.35805.5692
   437.3  807.43  459.51807.3605   484.8  805.87  491.88807.1323   500.6  813.17
   512.4  817.59   520.4  822.93   544.1  849.09     556  856.32   571.8  868.72
#Mann= 11 ,-1 , 0
       0     .12       0  114.26     .08       0  269.91     .12       0
     319    .045       0     334     .12       0  340.83     .08       0
  364.71    .016       0  412.11     .08       0  416.35    .016       0
  459.51     .06       0  491.88     .12       0
Bank Sta=319,334
XS Rating Curve= 0 ,0
Exp/Cntr=0.3,0.1

Type RM Length L Ch R = 1 ,14904.8 ,267.3,267.9,266.4
XS GIS Cut Line= 3
     1699332.954      361016.034     1699166.473      361257.593
     1698973.101      361506.589
#Sta/Elev= 30
       0  943.64    43.6  914.56    71.4  898.23    99.1  878.29     111   871.8
   190.3  822.04   241.8  798.14   269.6  794.51   285.9  788.43   293.4     787
   300.9   788.6  312.04 793.235   325.3  798.82  349.43798.8545   373.2  796.62
   385.2  793.38   389.2  793.89   397.1  797.38  424.23796.2274  453.43794.0048
  461.62 792.562   488.9  796.77   496.9  799.36   520.8  816.04   528.8  818.42
   540.8  818.43   548.8   820.8   556.8  825.54   588.7  837.28   608.6  851.44
#Mann= 8 ,-1 , 0
       0     .12       0   285.9    .045       0   300.9     .12       0
  312.04     .08       0  349.43    .016       0  424.23     .08       0
  453.43     .06       0  461.62     .12       0
#XS Ineff= 2 , 0
                          331.32          804.34
Permanent Ineff=
       F       F
Bank Sta=285.9,300.9
XS Rating Curve= 0 ,0
Exp/Cntr=0.3,0.1

Type RM Length L Ch R = 1 ,14636.9 ,414.2,418.4,422.1
XS GIS Cut Line= 2
     1699111.581      360871.021     1698751.339      361384.408
#Sta/Elev= 30
       0   903.1    51.9  883.51    79.9  874.73    99.9  866.06   139.8  843.04
   183.8  809.77   191.8  804.96   251.7  798.49   259.7  795.12   271.6  786.39
   287.6  786.73     292   785.2   299.6  782.62     307   784.6  332.47794.8175
  345.95796.3516  382.03793.3615   391.5  791.86  418.11793.9996  454.19790.6029
   467.4  790.66  490.28802.7632   495.3  806.13   503.3  808.64  526.36810.0218
  562.44811.8118  589.55813.3336   599.2  814.18   619.2  826.54   627.2  829.75
#Mann= 12 ,-1 , 0
       0     .12       0     292    .045       0     307     .12       0
  332.47     .08       0  345.95    .016       0  382.03     .08       0
  418.11    .016       0  454.19     .06       0  490.28    .016       0
  526.36     .06       0  562.44     .08       0  589.55     .06       0
Bank Sta=292,307
XS Rating Curve= 0 ,0
Exp/Cntr=0.3,0.1

Type RM Length L Ch R = 1 ,14218.5 ,450.8,437.3,423
XS GIS Cut Line= 2
     1698806.339      360671.068     1698354.553      361165.797
#Sta/Elev= 30
       0  937.43    87.7  895.59   167.5   848.9   187.4  833.25   207.4  806.59
   215.4  799.73   243.3  781.65   252.1  779.99   263.2   779.3   267.1   779.5
  268.54779.7494  294.33781.1915  312.34781.4868  334.33781.4102   350.9  785.23
  374.32785.4968  399.93788.8796  414.32791.9112  454.32791.5975   478.6  788.39
  487.53789.3416  494.32 790.323  534.32789.1044   558.3  786.09   602.2  792.38
   610.2  795.04  618.92801.9465   642.1  816.16  654.31 818.324     670  818.79
#Mann= 16 ,-1 , 0
       0     .12       0   252.1    .045       0   267.1     .12       0
  268.54     .06       0  294.33     .12       0  312.34     .06       0
  334.33     .12       0  374.32     .06       0  399.93     .08       0
  414.32    .016       0  454.32     .06       0  487.53     .08       0
  494.32    .016       0  534.32     .06       0  618.92     .12       0
  654.31     .06       0
Bank Sta=252.1,267.1
XS Rating Curve= 0 ,0
Exp/Cntr=0.3,0.1

Type RM Length L Ch R = 1 ,13781.3 ,315.6,318.3,318.1
XS GIS Cut Line= 4
     1698251.184      360540.836     1698218.924      360785.091
     1698296.702      360839.952     1698244.063      361144.807
#Sta/Elev= 30
       0  873.98    55.6  838.04    71.5  826.41    83.4  822.93    95.4  815.32
   123.2  804.71     155  796.17     159  794.02   174.8  780.75   194.7  778.21
   203.3  775.44   206.6   774.7   218.3  775.27   250.3  780.54  323.16782.0101
  390.74783.1375  420.71790.4135   452.6   790.1   476.4  786.97   496.2  789.51
  510.63788.8809   531.9  787.55   551.8   783.5   559.7  786.06   575.6  788.68
   583.5  791.69   607.3  796.27   615.2  798.73   623.2  802.97   650.9  823.74
#Mann= 7 ,-1 , 0
       0     .12       0   203.3    .045       0   218.3     .12       0
  323.16     .06       0  390.74     .08       0  420.71    .016       0
  510.63     .12       0
#XS Ineff= 2 , 0
                          253.65          782.81
Permanent Ineff=
       F       F
Bank Sta=203.3,218.3
XS Rating Curve= 0 ,0
Exp/Cntr=0.3,0.1

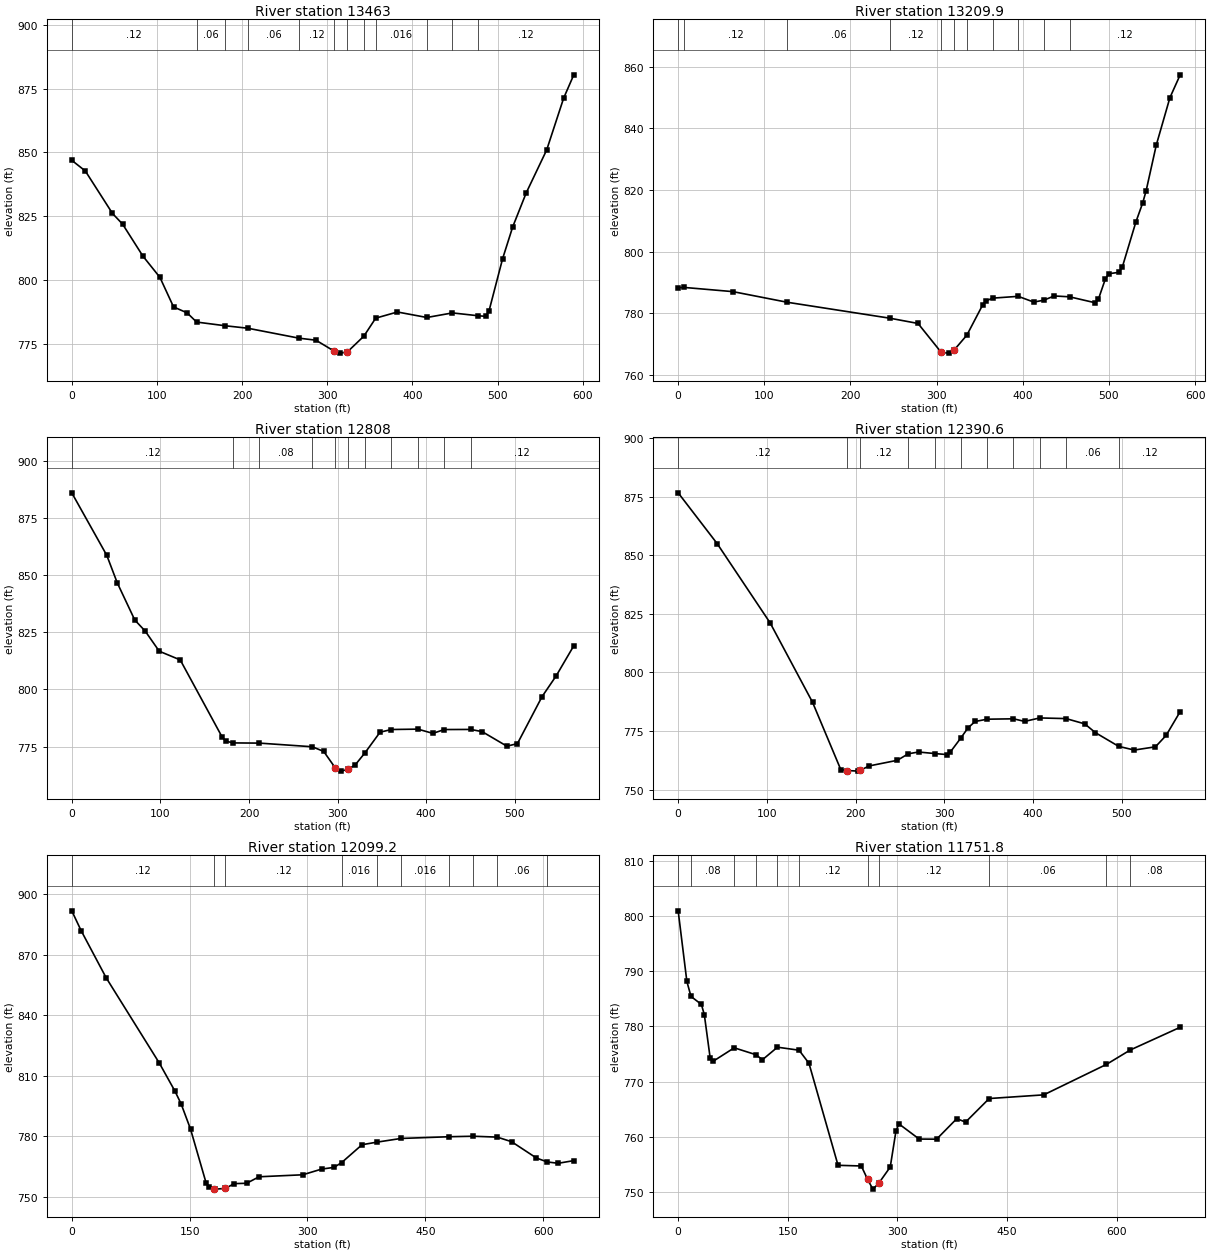
Type RM Length L Ch R = 1 ,13463   ,254,253.1,251.6
XS GIS Cut Line= 2
     1698037.718      360507.996     1697930.756      361087.616
#Sta/Elev= 30
       0  846.89    15.9  842.71    47.8  826.04    59.7  821.84    83.6  809.27
   103.5  800.96   119.5  789.37   135.4  787.04  146.59783.4283  180.23781.9761
  206.66781.0106  266.73777.1112   286.7  776.31   308.4  771.95   314.6  771.24
   323.4  771.65  342.94777.8979  356.83784.9584   382.3  787.38   416.9785.2242
  446.93787.0193  476.96 785.911   485.9  785.67   489.8   787.7   505.8  808.25
   517.7  820.78   533.6  834.15   557.6  850.97   577.5  871.28   589.4  880.43
#Mann= 12 ,-1 , 0
       0     .12       0  146.59     .06       0  180.23     .12       0
  206.66     .06       0  266.73     .12       0   308.4    .045       0
   323.4     .12       0  342.94     .08       0  356.83    .016       0
   416.9     .08       0  446.93    .016       0  476.96     .12       0
Bank Sta=308.4,323.4
XS Rating Curve= 0 ,0
Exp/Cntr=0.3,0.1

Type RM Length L Ch R = 1 ,13209.9 ,401,401.9,401.1
XS GIS Cut Line= 3
     1697775.738      360467.691      1697738.77      360743.571
     1697698.759      361045.268
#Sta/Elev= 30
       0  788.37    7.33 788.425    63.6  787.07  126.53783.6306  245.72 778.458
   278.4  776.76   305.3   767.4   313.9  767.14   320.3  768.14  335.11772.9703
   353.4  782.74   357.4  784.07   364.9784.9603   394.7785.5464   412.7  783.69
  424.49784.2982   436.4  785.67  454.28785.3952   483.9  783.47   487.8  784.63
   495.7  791.05   499.7  792.87   511.5  793.32   515.5     795   531.3  809.66
   539.2  815.82   543.2   819.8     555  834.62   570.8  849.95   582.7  857.34
#Mann= 11 ,-1 , 0
       0    .016       0    7.33     .12       0  126.53     .06       0
  245.72     .12       0   305.3    .045       0   320.3     .12       0
  335.11     .08       0   364.9    .016       0   394.7     .08       0
  424.49    .016       0  454.28     .12       0
Bank Sta=305.3,320.3
XS Rating Curve= 0 ,0
Exp/Cntr=0.3,0.1

Type RM Length L Ch R = 1 ,12808   ,417.8,417.4,413.6
XS GIS Cut Line= 3
      1697384.69      360412.751     1697346.408      360698.432
     1697309.827      360974.272
#Sta/Elev= 30
       0  886.03    39.5  858.69    51.3  846.68    71.1  830.38    82.9  825.52
    98.7  816.73   122.4  812.92   169.8  779.09   173.7  777.43  181.97776.6026
  211.77776.5197  271.37774.9222   284.3  772.88   297.2  765.76   304.1  764.26
   312.2  765.12     320  767.05  330.96 772.308   347.9   781.3  360.76782.4712
  390.55782.6351   407.5  780.78  420.34782.4546  450.14782.5012   463.1  781.54
     491  775.18   502.9  776.29   530.7  796.86   546.6  805.92   566.5   819.1
#Mann= 11 ,-1 , 0
       0     .12       0  181.97    .016       0  211.77     .08       0
  271.37     .12       0   297.2    .045       0   312.2     .12       0
  330.96     .08       0  360.76    .016       0  390.55     .08       0
  420.34    .016       0  450.14     .12       0
Bank Sta=297.2,312.2
XS Rating Curve= 0 ,0
Exp/Cntr=0.3,0.1

Type RM Length L Ch R = 1 ,12390.6 ,304.3,291.4,274.9
XS GIS Cut Line= 2
     1697019.231      360364.194     1696968.855      360928.083
#Sta/Elev= 30
       0  876.66    43.9  855.02   103.7  821.14   151.5  787.27   183.4  758.48
   190.3  758.11   203.3  757.85   205.3  758.19   215.3  760.06   247.2  762.48
   259.5765.2538   271.1  766.01  289.15765.3588     303  764.92     307  766.05
  318.81772.0198   326.9  776.34   334.9  779.05  348.46 780.018  378.11780.1859
   390.7  779.08  407.76780.5564  437.42780.2789   458.5  778.02   470.4   774.3
  496.72768.4262   514.3  766.85   538.2  768.23   550.2  773.07   566.1  783.26
#Mann= 11 ,-1 , 0
       0     .12       0   190.3    .045       0   205.3     .12       0
   259.5    .016       0  289.15     .06       0  318.81     .08       0
  348.46    .016       0  378.11     .08       0  407.76    .016       0
  437.42     .06       0  496.72     .12       0
Bank Sta=190.3,205.3
XS Rating Curve= 0 ,0
Exp/Cntr=0.3,0.1

Type RM Length L Ch R = 1 ,12099.2 ,370.7,347.4,323.5
XS GIS Cut Line= 5
     1696632.478       360412.87     1696701.228      360560.787
     1696722.755      360603.148     1696878.593      360634.136
     1696950.784      360893.814
#Sta/Elev= 30
       0  891.87    11.9  882.05    43.8  858.63   111.4  816.33   131.3   802.4
   139.2  796.04   151.2  783.49     171   756.8     175  754.85   180.6  753.84
   182.9  753.73   195.6  754.09   206.7  756.45   222.6  756.64   238.4  759.86
     294  760.85   317.9  763.66   333.8  764.53  343.58766.9198   369.5  775.78
  388.27777.0356  418.93778.8792  480.24779.7352  510.89779.9864  541.55779.5443
   559.8  777.28   591.5  769.16  605.38767.2078   619.2  766.56     639  767.88
#Mann= 10 ,-1 , 0
       0     .12       0   180.6    .045       0   195.6     .12       0
  343.58    .016       0  388.27     .08       0  418.93    .016       0
  480.24     .08       0  510.89    .016       0  541.55     .06       0
  605.38     .12       0
Bank Sta=180.6,195.6
XS Rating Curve= 0 ,0
Exp/Cntr=0.3,0.1

Type RM Length L Ch R = 1 ,11751.8 ,239.8,278.2,319.7
XS GIS Cut Line= 4
     1696387.874      360546.088     1696398.291      360780.463
     1696669.133       360817.72     1696743.777      360980.115
#Sta/Elev= 30
       0  800.96    11.9  788.15   17.55785.4335    31.8  783.98    35.8  782.11
    43.7  774.34    47.7  773.66   76.68776.1133  106.24774.8704   115.3  773.95
  135.81776.2239  165.37775.6778   178.9  773.31   218.7   754.8   250.5  754.68
   259.2  752.23   266.3  750.48   274.2  751.51   290.1  754.49     298  761.08
     302  762.31   329.7  759.56   353.5  759.54   381.2  763.27   393.1  762.63
  425.44766.9128   500.1  767.58  585.89773.1077  618.39775.7155   686.7  779.84
#Mann= 11 ,-1 , 0
       0     .12       0   17.55     .08       0   76.68    .016       0
  106.24     .08       0  135.81    .016       0  165.37     .12       0
   259.2    .045       0   274.2     .12       0  425.44     .06       0
  585.89    .016       0  618.39     .08       0
Bank Sta=259.2,274.2
XS Rating Curve= 0 ,0
Exp/Cntr=0.3,0.1

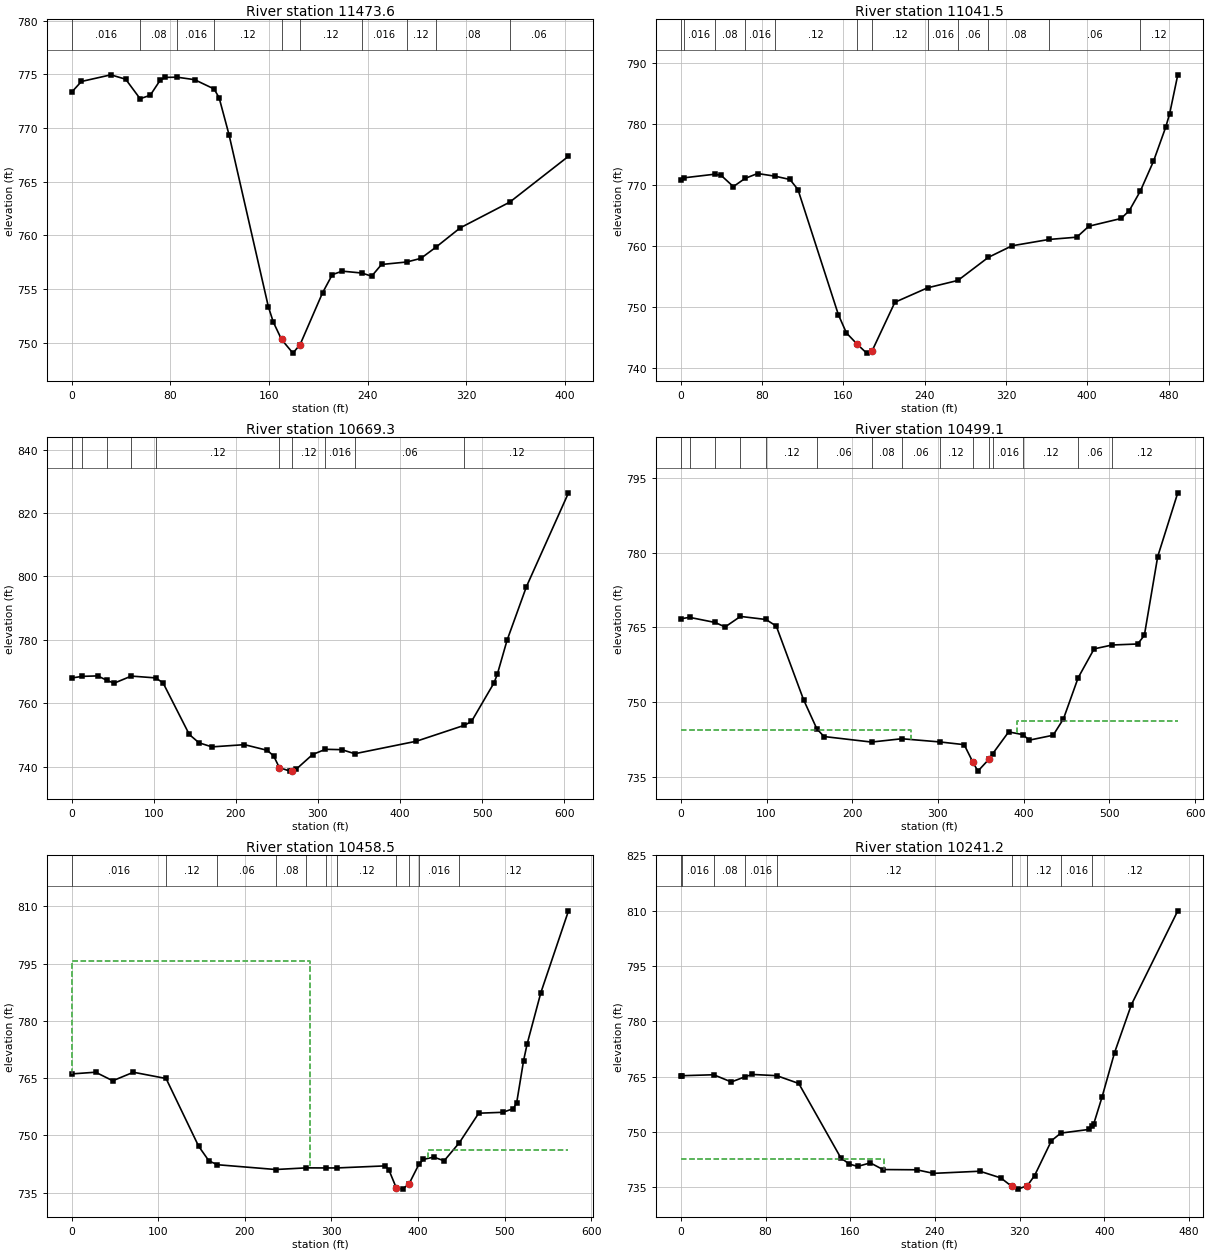
Type RM Length L Ch R = 1 ,11473.6 ,432.1,432.1,431.3
XS GIS Cut Line= 2
     1696189.488      360567.893     1696122.524      360965.003
#Sta/Elev= 30
       0  773.32       8  774.33    31.9  774.95    43.9  774.54   55.58772.7248
    63.8  773.05    71.8  774.44    75.8  774.71   85.53  774.73    99.7   774.5
  115.48773.6378   119.6  772.82   127.6  769.39   159.5  753.37   163.5  751.94
   170.2  750.32   179.4  749.05   185.2  749.84   203.4  754.66   211.3  756.35
   219.3  756.68  235.29756.5037   243.2  756.21   251.2   757.3   271.6  757.53
   283.1  757.87   295.2758.9018     315  760.71   355.1 763.102   402.7  767.37
#Mann= 10 ,-1 , 0
       0    .016       0   55.58     .08       0   85.53    .016       0
  115.48     .12       0   170.2    .045       0   185.2     .12       0
  235.29    .016       0   271.6     .12       0   295.2     .08       0
   355.1     .06       0
Bank Sta=170.2,185.2
XS Rating Curve= 0 ,0
Exp/Cntr=0.3,0.1

Type RM Length L Ch R = 1 ,11041.5 ,389.6,372.2,354.6
XS GIS Cut Line= 2
     1695766.031      360501.195      1695687.78      360983.969
#Sta/Elev= 30
       0  770.87    3.43771.2387   33.35771.8267    39.8  771.62    51.7  769.79
   63.27771.1399    75.6  771.94   93.19771.4853   107.4  770.96   115.3  769.31
   155.1  748.78     163   745.8   173.3     744   182.9  742.49   188.3  742.87
   210.7  750.83  242.79753.1934  272.71754.4086  302.63758.1898     326  760.09
  362.47761.1301   389.7   761.5   401.6   763.3   433.4  764.57   441.4  765.86
  452.24769.0549   465.2  773.95   477.2  779.52   481.1  781.74   489.1  788.12
#Mann= 12 ,-1 , 0
       0     .08       0    3.43    .016       0   33.35     .08       0
   63.27    .016       0   93.19     .12       0   173.3    .045       0
   188.3     .12       0  242.79    .016       0  272.71     .06       0
  302.63     .08       0  362.47     .06       0  452.24     .12       0
Bank Sta=173.3,188.3
XS Rating Curve= 0 ,0
Exp/Cntr=0.3,0.1

Type RM Length L Ch R = 1 ,10669.3 ,169.7,170.2,170
XS GIS Cut Line= 4
     1695328.651      360432.304     1695311.702      360574.674
     1695474.897      360812.521     1695460.227      360985.169
#Sta/Elev= 30
       0  767.98   13.32768.4969    31.9  768.64   43.06767.2466    51.8  766.34
   72.81768.5811  102.55768.0056   111.5  766.42   143.4  750.16   155.2  747.54
     171  746.25   210.6  746.95   238.2  745.17   246.1  743.41     253  739.72
   265.9   738.6     268  738.72   273.8  739.26   293.5  743.83  309.12745.4838
   329.1  745.37  344.93744.0908     420  748.04  478.48753.0726     487  754.27
   514.5  766.47   518.5   769.2   530.3  779.87   553.9   796.8   605.1  826.39
#Mann= 10 ,-1 , 0
       0     .08       0   13.32    .016       0   43.06     .08       0
   72.81    .016       0  102.55     .12       0     253    .045       0
     268     .12       0  309.12    .016       0  344.93     .06       0
  478.48     .12       0
Bank Sta=253,268
XS Rating Curve= 0 ,0
Exp/Cntr=0.3,0.1

Type RM Length L Ch R = 1 ,10499.1 ,40.9,40.6,40.4
XS GIS Cut Line= 4
     1695160.592      360405.833       1695140.4      360599.641
     1695295.906       360836.66     1695252.425       360928.33
#Sta/Elev= 30
       0  766.71   10.22766.9927   39.92765.9706    51.7  765.07   69.61767.1799
   99.31766.5659   111.4  765.24   143.2  750.48   158.7  744.64     167  743.09
  222.49  741.98  257.81742.6435  302.06 742.008   330.6  741.46  340.61     738
   346.6  736.15   359.3   738.5  363.78 739.623   382.5  744.02  399.11743.4697
   406.5  742.36   434.4  743.35   446.4  746.62  463.59754.8845   482.2  760.67
  503.08 761.447     533  761.65   540.8  763.38   556.4  779.19   579.8  791.97
#Mann= 15 ,-1 , 0
       0     .08       0   10.22    .016       0   39.92     .08       0
   69.61    .016       0   99.31     .12       0   158.7     .06       0
  222.49     .08       0  257.81     .06       0  302.06     .12       0
  340.61    .045       0   359.3     .12       0  363.78    .016       0
  399.11     .12       0  463.59     .06       0  503.08     .12       0
#XS Ineff= 2 , 0
          268.82  744.38  391.85          746.16
Permanent Ineff=
       F       F
Bank Sta=340.61,359.3
XS Rating Curve= 0 ,0
Exp/Cntr=0.3,0.1

Type RM Length L Ch R = 1 ,10458.5 ,202.6,217.4,232.3
XS GIS Cut Line= 4
     1695097.565      360395.905     1695081.527      360581.595
     1695237.052      360818.643     1695191.318      360911.616
#Sta/Elev= 30
       0  766.09    27.8  766.54    47.6   764.3    71.4  766.53  109.11764.8943
   146.7  747.15   158.6   743.3   168.4742.3023   235.6 741.049  270.92741.4818
  293.22741.4572  306.25  741.46   362.1     742   366.1  741.03   374.6  736.33
     382  735.91   389.6  737.33  400.91742.4195     406  743.69     418   744.3
     430  743.33  447.54748.0624   469.9   755.8   497.8  756.04   509.8  756.99
   513.7  758.53   521.7   769.6   525.7  773.87   541.6  787.38   573.5  808.82
#Mann= 11 ,-1 , 0
       0    .016       0  109.11     .12       0   168.4     .06       0
   235.6     .08       0  270.92     .06       0  293.22     .08       0
  306.25     .12       0   374.6    .045       0   389.6     .12       0
  400.91    .016       0  447.54     .12       0
#XS Ineff= 2 , 0
          274.72  795.61  411.24          746.22
Permanent Ineff=
       F       F
Bank Sta=374.6,389.6
XS Rating Curve= 0 ,0
Exp/Cntr=0.3,0.1

Type RM Length L Ch R = 1 ,10241.2 ,434.4,435.6,436.5
XS GIS Cut Line= 2
     1695029.591      360385.199     1694967.262      360850.331
#Sta/Elev= 30
       0  765.17    1.29765.2377   31.08765.4944    47.7  763.54   60.88764.9745
    67.6  765.58   90.68 765.243   111.4  763.13   151.1  742.94   159.1  741.26
     167  740.63     179  741.58   190.9  739.77   222.7  739.71   238.6  738.74
   282.4  739.32   302.2   737.5   312.3  735.26   318.2  734.46   327.3  735.41
   334.1  738.15     350   747.6  358.87749.6636   385.8  750.67  388.67 751.653
   389.8  752.04   397.7  759.36   409.6   771.5   425.5  784.51   469.3  809.98
#Mann= 9 ,-1 , 0
       0     .08       0    1.29    .016       0   31.08     .08       0
   60.88    .016       0   90.68     .12       0   312.3    .045       0
   327.3     .12       0  358.87    .016       0  388.67     .12       0
#XS Ineff= 2 , 0
          191.71   742.7
Permanent Ineff=
       F       F
Bank Sta=312.3,327.3
XS Rating Curve= 0 ,0
Exp/Cntr=0.3,0.1

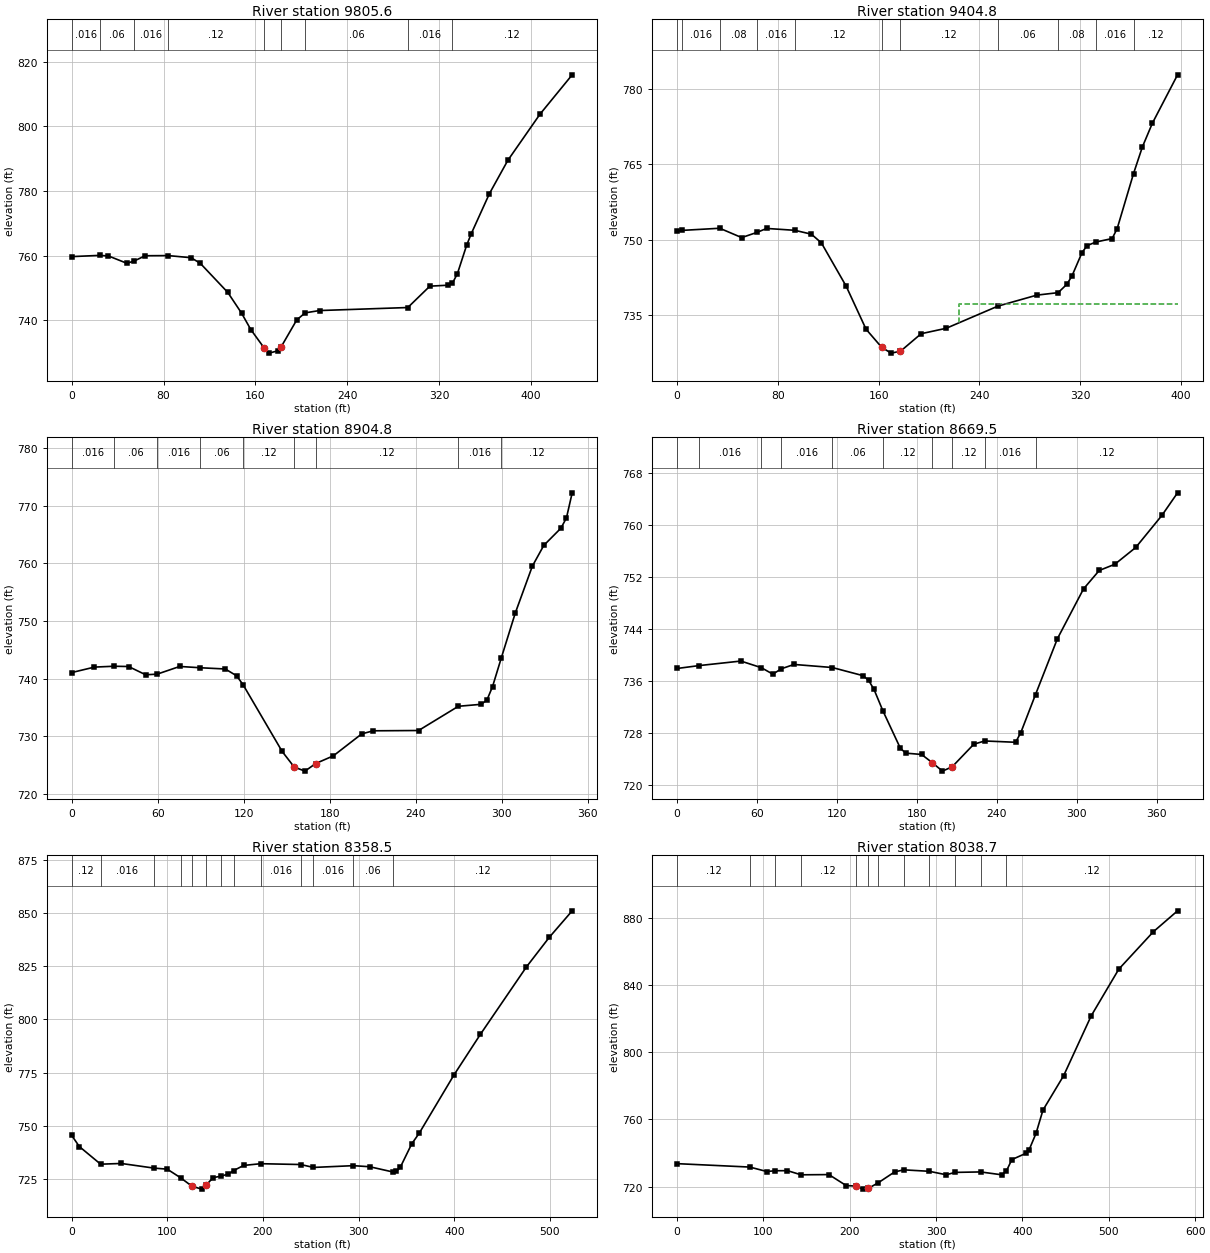
Type RM Length L Ch R = 1 ,9805.6  ,400.2,400.8,400.6
XS GIS Cut Line= 2
     1694711.608      360332.749     1694653.743      360764.577
#Sta/Elev= 30
       0  759.69   24.42760.0695      32  759.89      48  757.63   54.22758.3052
      64  759.96   84.02760.0058   103.9  759.35   111.9  757.63   135.9  748.61
   147.9   742.2   155.9  737.14   167.4  731.51   171.9  729.84   179.9   730.6
   182.4  731.81   195.9   740.1  203.21 742.295   215.8  743.01  292.61743.9421
   311.8  750.55   327.8  750.85  331.51751.5085   335.8  754.43   343.8  763.18
   347.8  766.74   363.7   779.2   379.7  789.47   407.7  803.75   435.7  815.91
#Mann= 9 ,-1 , 0
       0    .016       0   24.42     .06       0   54.22    .016       0
   84.02     .12       0   167.4    .045       0   182.4     .12       0
  203.21     .06       0  292.61    .016       0  331.51     .12       0
Bank Sta=167.4,182.4
XS Rating Curve= 0 ,0
Exp/Cntr=0.3,0.1

Type RM Length L Ch R = 1 ,9404.8  ,498.5,500,500.3
XS GIS Cut Line= 3
     1694319.175      360264.343      1694296.74      360432.619
     1694261.577       360657.31
#Sta/Elev= 30
       0  751.63    4.06751.8328   33.85752.2565    51.3   750.4   63.65751.4565
    71.1  752.22   93.45751.8474   106.6  751.08   114.5  749.36   134.2  740.74
     150  732.18   162.3  728.61   169.8  727.43   177.3   727.8   193.7  731.29
   213.6  732.37  254.62736.7754   285.5  738.96  302.46739.4545   309.4  741.13
   313.4  742.77   321.4  747.43   325.4   748.8  332.35 749.516   345.3  750.21
   349.3   752.2  362.25763.1214   369.3  768.43   377.2  773.13   397.2  782.76
#Mann= 11 ,-1 , 0
       0     .08       0    4.06    .016       0   33.85     .08       0
   63.65    .016       0   93.45     .12       0   162.3    .045       0
   177.3     .12       0  254.62     .06       0  302.46     .08       0
  332.35    .016       0  362.25     .12       0
#XS Ineff= 2 , 0
                           223.6          737.23
Permanent Ineff=
       F       F
Bank Sta=162.3,177.3
XS Rating Curve= 0 ,0
Exp/Cntr=0.3,0.1

Type RM Length L Ch R = 1 ,8904.8  ,222.4,235.3,247.3
XS GIS Cut Line= 3
     1693837.073      360180.307     1693807.268      360340.314
     1693773.107      360523.702
#Sta/Elev= 30
       0  741.04    15.9  741.99   29.51742.1357    39.7  742.09    51.6  740.66
   59.55740.7579    75.4   742.1    89.6741.8768   107.2  741.66   115.1  740.48
  119.64 738.918   146.9  727.34   155.3  724.64   162.8  723.93   170.3  725.25
   182.6  726.58   202.4  730.39   210.4  730.93   242.1  730.98  269.85735.1857
   285.8  735.53   289.8  736.27   293.7  738.59   299.9 743.632   309.6  751.38
   321.5  759.51   329.5  763.12   341.4  766.09   345.3  767.88   349.3  772.24
#Mann= 9 ,-1 , 0
       0    .016       0   29.51     .06       0   59.55    .016       0
    89.6     .06       0  119.64     .12       0   155.3    .045       0
   170.3     .12       0  269.85    .016       0   299.9     .12       0
Bank Sta=155.3,170.3
XS Rating Curve= 0 ,0
Exp/Cntr=0.3,0.1

Type RM Length L Ch R = 1 ,8669.5  ,309.3,311,313.1
XS GIS Cut Line= 3
     1693703.446      360148.759     1693589.603      360287.797
     1693465.367      360439.528
#Sta/Elev= 30
       0  737.96   16.63738.4063    47.9   739.1   63.25738.0861    71.9  737.09
   78.28737.9114    87.8  738.58  116.45738.1102   139.8  736.85   143.8  736.14
   147.8  734.78  154.63731.4242   167.7   725.7   171.7  724.96   183.6  724.76
   191.6   723.5   199.3   722.2   206.6  722.87   222.8  726.33  230.97726.8317
   254.2  726.63   258.1  728.11  269.15  733.96   285.6  742.54   305.2  750.18
     317  753.01   328.7  753.96   344.4  756.54     364  761.45   375.8  764.93
#Mann= 10 ,-1 , 0
       0     .08       0   16.63    .016       0   63.25     .08       0
   78.28    .016       0  116.45     .06       0  154.63     .12       0
   191.6    .045       0   206.6     .12       0  230.97    .016       0
  269.15     .12       0
Bank Sta=191.6,206.6
XS Rating Curve= 0 ,0
Exp/Cntr=0.3,0.1

Type RM Length L Ch R = 1 ,8358.5  ,334.7,319.8,303.8
XS GIS Cut Line= 2
     1693477.967      359971.194     1693108.638      360341.955
#Sta/Elev= 30
       0  745.51       8  740.28   30.24731.9984    51.9  732.33   86.01730.1536
    99.9  729.66  113.94725.5948   125.5  721.72   135.8  720.28   140.5  722.15
   147.8  725.65  155.78726.3586   163.8  727.34  169.39729.0151   179.8  731.41
  197.63732.2213  239.48731.8361  252.77730.4678  294.46   731.3   311.6   730.8
  336.15728.3022   339.6  728.63   343.6  730.55   355.5  741.51   363.5  746.64
   399.5  773.76   427.4  793.03   475.4   824.6   499.4  838.57   523.3  850.99
#Mann= 13 ,-1 , 0
       0     .12       0   30.24    .016       0   86.01     .06       0
  113.94     .12       0   125.5    .045       0   140.5     .08       0
  155.78     .12       0  169.39     .08       0  197.63    .016       0
  239.48     .08       0  252.77    .016       0  294.46     .06       0
  336.15     .12       0
Bank Sta=125.5,140.5
XS Rating Curve= 0 ,0
Exp/Cntr=0.3,0.1

Type RM Length L Ch R = 1 ,8038.7  ,424.1,422.8,420.8
XS GIS Cut Line= 2
     1693098.359      359800.699     1693037.158      360377.147
#Sta/Elev= 30
       0  733.75   84.24 731.724   103.9  729.08  113.94729.5387   127.9  729.58
  143.64727.1227   175.9  727.25   195.9  720.72   206.7  720.46   215.9  718.61
   221.7  719.12  232.75722.2957   251.9  728.81  262.45730.0784  292.15729.2051
   311.8  727.14  321.85728.5558  351.55728.8306   375.8  727.14  381.25729.1849
   387.8  736.17   403.8  739.83   407.8  742.02   415.8  751.79   423.8  765.57
   447.8  786.08   479.7  821.63   511.7  849.39   551.7   871.6   579.7  884.02
#Mann= 12 ,-1 , 0
       0     .12       0   84.24     .08       0  113.94    .016       0
  143.64     .12       0   206.7    .045       0   221.7     .12       0
  232.75     .08       0  262.45    .016       0  292.15     .08       0
  321.85    .016       0  351.55     .06       0  381.25     .12       0
Bank Sta=206.7,221.7
XS Rating Curve= 0 ,0
Exp/Cntr=0.3,0.1

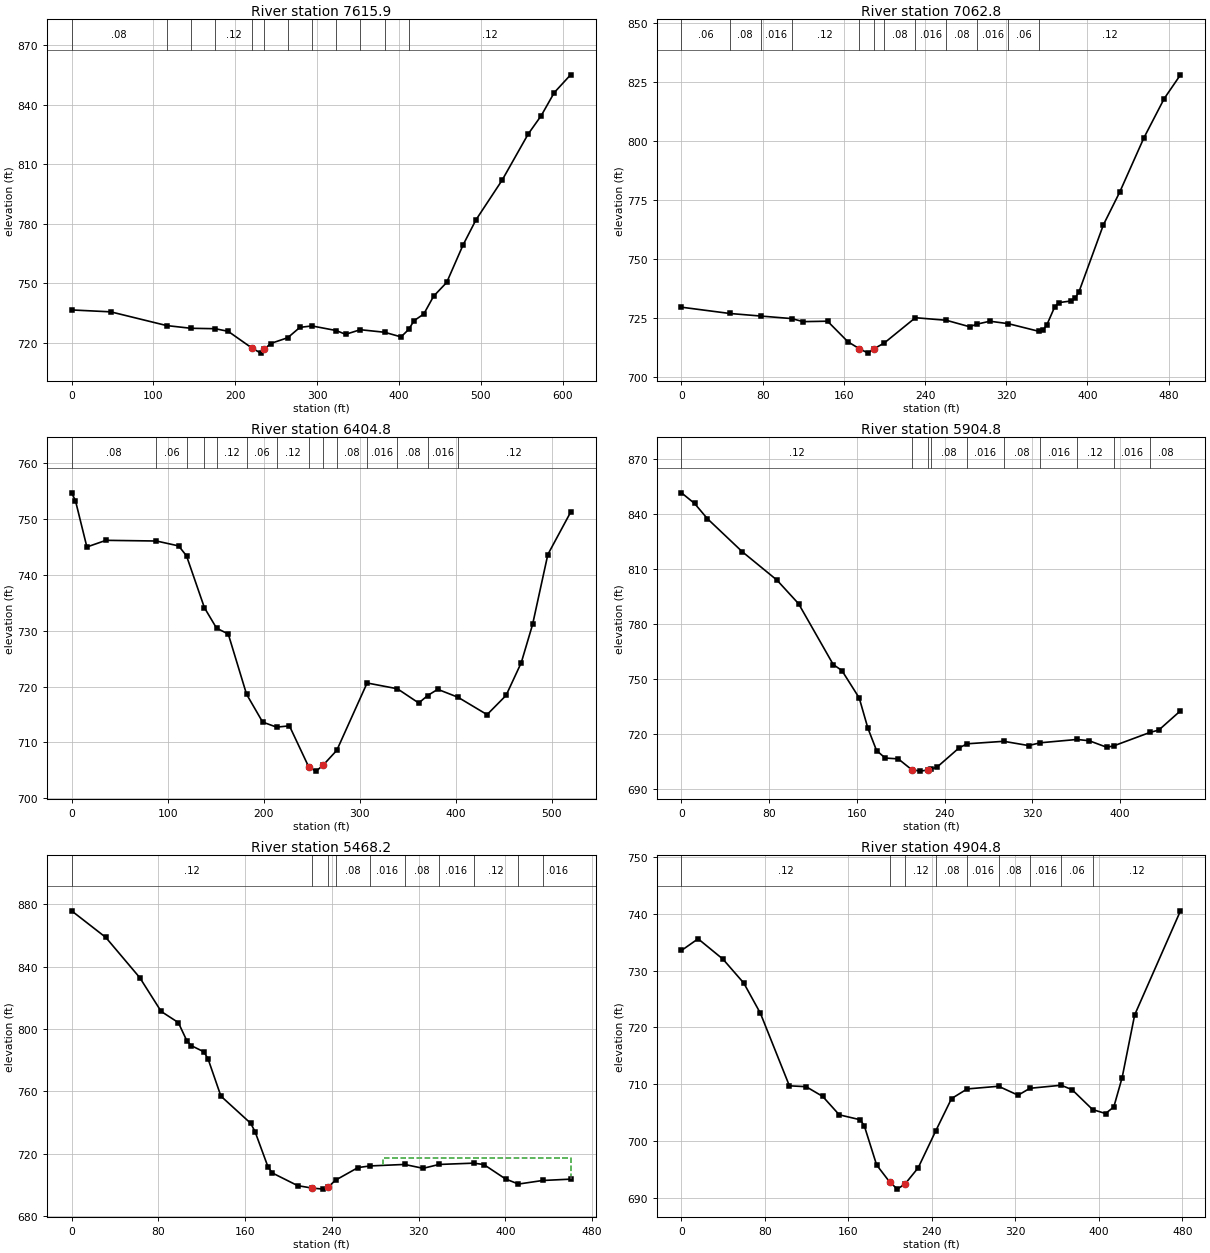
Type RM Length L Ch R = 1 ,7615.9  ,558.9,553.1,545.4
XS GIS Cut Line= 2
     1692671.969      359738.889      1692639.54      360347.829
#Sta/Elev= 30
       0  736.49    47.8  735.53  116.23728.5975  145.81727.2349  175.38727.0204
   191.3  725.71   220.7  717.17   231.2   714.7   235.7  716.66   243.1  719.54
  264.11722.4713     279   727.7  293.69728.4224  323.27726.1066   334.8  724.19
  352.84726.5109  382.42725.2303   402.6  722.89     412  726.68   418.5  731.07
   430.4  734.44   442.4  743.42   458.4  750.38   478.3  769.19   494.2  781.97
   526.1  801.95     558  825.26   573.9  834.51   589.9  846.18   609.8  855.12
#Mann= 12 ,-1 , 0
       0     .08       0  116.23     .12       0  145.81    .016       0
  175.38     .12       0   220.7    .045       0   235.7     .12       0
  264.11     .08       0  293.69    .016       0  323.27     .08       0
  352.84    .016       0  382.42     .06       0     412     .12       0
Bank Sta=220.7,235.7
XS Rating Curve= 0 ,0
Exp/Cntr=0.3,0.1

Type RM Length L Ch R = 1 ,7062.8  ,659,658,654.5
XS GIS Cut Line= 2
     1692069.563       359838.48     1692191.353      360314.783
#Sta/Elev= 30
       0  729.44   47.52726.7836      78725.6953  108.49 724.618   119.9  723.32
   143.9  723.51   163.9  714.82   174.9  711.92   183.9  709.98   189.9  711.88
  199.94 714.326  230.42724.9827  260.91723.9012   283.8  721.17  291.39 722.288
   303.8   723.5  321.88722.4688  352.36719.1909   355.7   719.6   359.7  721.71
   367.7  729.58   371.7  731.38   383.7  732.07   387.7  733.16   391.7  736.08
   415.7  764.38   431.7  778.17   455.6  801.24   475.6  817.85   491.6  827.91
#Mann= 12 ,-1 , 0
       0     .06       0   47.52     .08       0      78    .016       0
  108.49     .12       0   174.9    .045       0   189.9     .12       0
  199.94     .08       0  230.42    .016       0  260.91     .08       0
  291.39    .016       0  321.88     .06       0  352.36     .12       0
Bank Sta=174.9,189.9
XS Rating Curve= 0 ,0
Exp/Cntr=0.3,0.1

Type RM Length L Ch R = 1 ,6404.8  ,502.7,500,496.7
XS GIS Cut Line= 3
     1691402.774      359948.716     1691486.553      360189.313
     1691580.048      360437.319
#Sta/Elev= 30
       0  754.66       4  753.26    15.9  744.97    35.8  746.16   88.42746.0367
   111.5  745.16  119.69743.3824  138.34734.1036  150.97730.4504   163.2  729.39
  182.24  718.62     199  713.64  213.51712.7318   226.9  712.96   247.3  705.51
   254.8  704.86   262.3  705.98  276.26708.5854  307.82720.6332  339.39719.5967
   361.6  717.05  370.95  718.39   381.4   719.5  402.51718.0818   432.8  714.97
   452.6  718.41   468.4  724.26   480.2   731.1   496.1  743.62   519.8  751.18
#Mann= 14 ,-1 , 0
       0     .08       0   88.42     .06       0  119.69     .12       0
  138.34     .06       0  150.97     .12       0  182.24     .06       0
  213.51     .12       0   247.3    .045       0   262.3     .12       0
  276.26     .08       0  307.82    .016       0  339.39     .08       0
  370.95    .016       0  402.51     .12       0
Bank Sta=247.3,262.3
XS Rating Curve= 0 ,0
Exp/Cntr=0.3,0.1

Type RM Length L Ch R = 1 ,5904.8  ,434.2,436.6,438.7
XS GIS Cut Line= 3
       1690939.7      360214.013     1691038.776      360407.579
      1691149.68      360617.753
#Sta/Elev= 30
       0   851.7    11.9   845.9    23.7  837.55    55.4  819.58      87  804.12
   106.8  791.19   138.4  758.02   146.3  754.75   162.1  739.78     170   723.3
   177.9  711.12   185.8     707   197.7  706.56   209.9   700.7   217.4  699.87
   224.9  700.46  227.18700.8221   233.3  702.16   253.1  712.51  260.57714.7851
  293.97716.1376   316.5  713.82  327.36715.3388  360.76  717.15   371.9  716.44
   387.8   712.9  394.15713.6311  427.54721.0444   435.3  722.25   455.1  732.78
#Mann= 10 ,-1 , 0
       0     .12       0   209.9    .045       0   224.9     .12       0
  227.18     .08       0  260.57    .016       0  293.97     .08       0
  327.36    .016       0  360.76     .12       0  394.15    .016       0
  427.54     .08       0
Bank Sta=209.9,224.9
XS Rating Curve= 0 ,0
Exp/Cntr=0.3,0.1

Type RM Length L Ch R = 1 ,5468.2  ,559.8,563.4,567.6
XS GIS Cut Line= 3
     1690556.021      360367.662     1690639.912      360575.607
     1690727.867        360794.6
#Sta/Elev= 30
       0  875.66    31.5  858.65    62.9  832.83    82.6  811.23    98.4  804.11
   106.2  792.56   110.2  789.38     122  785.37   125.9  780.72   137.7  756.99
   165.2  739.57   169.2   734.2     181   711.9   184.9  707.86   208.5  699.67
   221.7  698.12   232.2  697.44   236.7  698.81  243.42703.1759   264.2  711.26
  275.25712.2854  307.07713.2504   324.2  710.76   338.9713.2402  370.73714.0767
   380.2  713.19   400.2  703.96   412.1700.6862  434.38 702.968   460.2  703.83
#Mann= 10 ,-1 , 0
       0     .12       0   221.7    .045       0   236.7     .12       0
  243.42     .08       0  275.25    .016       0  307.07     .08       0
   338.9    .016       0  370.73     .12       0   412.1     .06       0
  434.38    .016       0
#XS Ineff= 2 , 0
                          287.22           717.6
Permanent Ineff=
       F       F
Bank Sta=221.7,236.7
XS Rating Curve= 0 ,0
Exp/Cntr=0.3,0.1

Type RM Length L Ch R = 1 ,4904.8  ,427.6,427.5,425.6
XS GIS Cut Line= 3
     1690055.812      360533.608     1690105.816      360734.367
     1690155.143      361001.126
#Sta/Elev= 30
       0  733.54    15.9  735.59    39.8     732    59.7   727.8    75.6   722.5
   103.4  709.73   119.4  709.58   135.3  707.87   151.2  704.63   171.1  703.77
   175.1  702.75     187  695.81   199.4  692.84   206.9  691.56   214.4   692.5
   226.8   695.3  243.79701.8514   258.8  707.49  273.82709.1826  303.86709.6531
   322.6  708.08  333.89709.2948  363.93709.8328   374.4  709.04  393.96705.5573
   406.4  704.86   414.3  706.01   422.3  711.18   434.3   722.2   478.2  740.51
#Mann= 9 ,-1 , 0
       0     .12       0   199.4    .045       0   214.4     .12       0
  243.79     .08       0  273.82    .016       0  303.86     .08       0
  333.89    .016       0  363.93     .06       0  393.96     .12       0
Bank Sta=199.4,214.4
XS Rating Curve= 0 ,0
Exp/Cntr=0.3,0.1