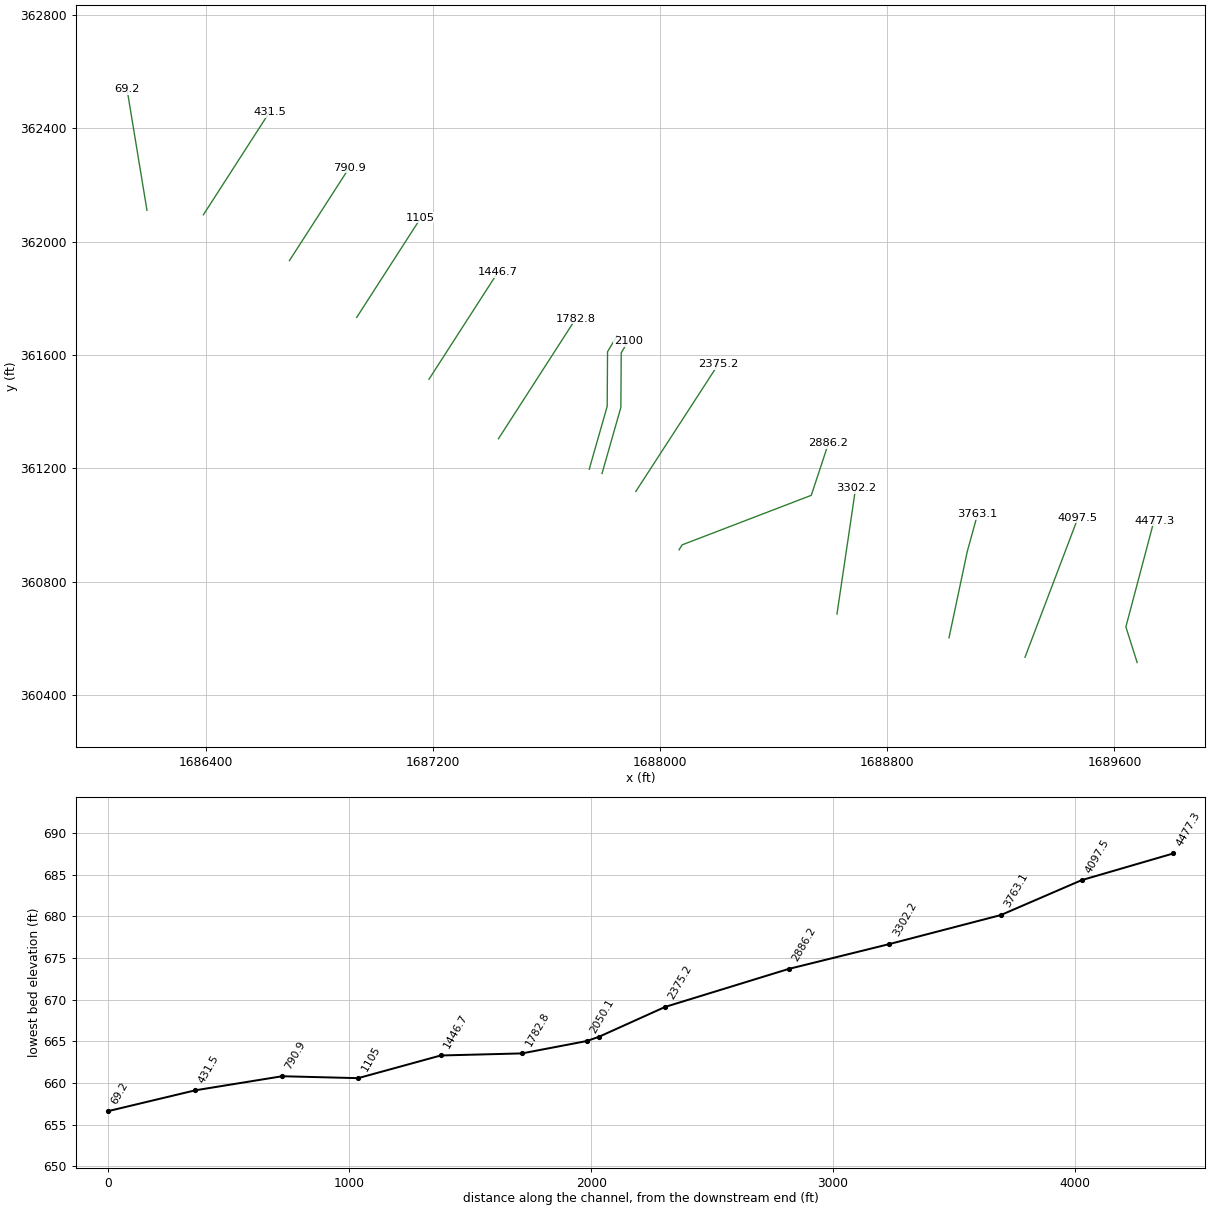
HEC-RAS study TRACEFK.prj: TRACEFK

--- TRACEFK.g01 (geometry) --- (continued)

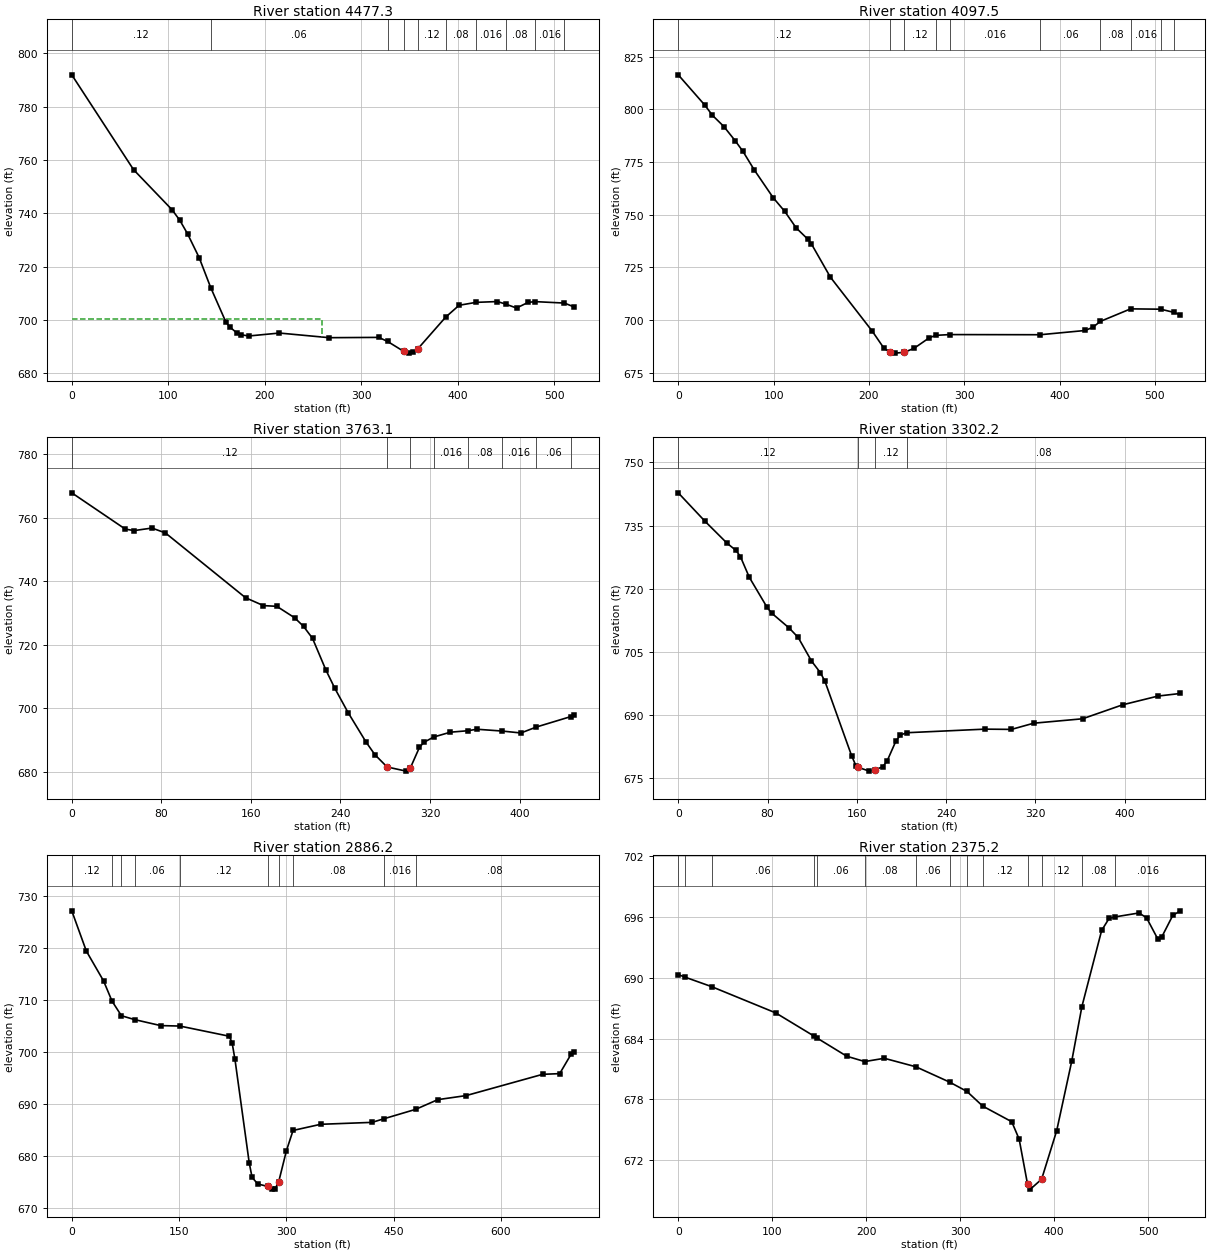
Type RM Length L Ch R = 1 ,4477.3  ,382.6,379.7,376.4
XS GIS Cut Line= 3
     1689680.182      360515.058     1689640.464      360640.936
     1689739.727       361016.37
#Sta/Elev= 30
       0  791.92      64  756.37     104   741.3     112  737.35     120   732.3
     132  723.39  143.99712.1371   159.7  699.23   163.7  697.39   171.6  694.98
   175.6  694.46   183.5     694   215.2   695.1   266.7  693.36   318.2  693.47
  327.28691.9474   343.8  688.27   349.9  687.57   353.9  687.81   358.8  689.26
  387.43701.0516   401.4  705.51  418.93 706.603   441.1  706.91  449.48705.9772
   460.9  704.48   472.8  706.58  480.03 706.885  510.58706.3365   520.3  704.92
#Mann= 10 ,-1 , 0
       0     .12       0  143.99     .06       0  327.28     .12       0
   343.8    .045       0   358.8     .12       0  387.43     .08       0
  418.93    .016       0  449.48     .08       0  480.03    .016       0
  510.58     .12       0
#XS Ineff= 2 , 0
          259.55   700.2
Permanent Ineff=
       F       F
Bank Sta=343.8,358.8
XS Rating Curve= 0 ,0
Exp/Cntr=0.3,0.1

Type RM Length L Ch R = 1 ,4097.5  ,330.4,334.4,337.1
XS GIS Cut Line= 2
     1689285.173      360533.752     1689471.796      361026.203
#Sta/Elev= 30
       0  816.41    27.9  802.02    35.9  797.18    47.9  791.86    59.8  785.09
    67.8  780.14    79.8  771.25    99.7  758.04   111.7  751.62   123.7  743.78
   135.6  738.56   139.6  736.24   159.6  720.39   203.5  694.78   215.4  686.92
     222   684.7   227.4  684.36     237  684.73   247.4  686.66   263.3  691.64
  270.05692.7957  284.95693.1592   379.7693.0915   426.9  695.11   434.9  696.65
  442.87699.4389  474.46 705.363  506.04 705.205  520.11703.6678   526.6  702.49
#Mann= 10 ,-1 , 0
       0     .12       0     222    .045       0     237     .12       0
  270.05     .08       0  284.95    .016       0   379.7     .06       0
  442.87     .08       0  474.46    .016       0  506.04     .06       0
  520.11     .08       0
Bank Sta=222,237
XS Rating Curve= 0 ,0
Exp/Cntr=0.3,0.1

Type RM Length L Ch R = 1 ,3763.1  ,458.8,461,462.5
XS GIS Cut Line= 3
     1689017.475      360602.393     1689081.648      360906.188
     1689118.179      361039.179
#Sta/Elev= 30
       0  767.79    47.8  756.37    55.7   755.9    71.6   756.7    83.6  755.17
   155.2  734.76   171.2  732.28   183.1  732.06     199  728.46     207  725.74
     215  721.98   226.9  712.05   234.9  706.26   246.8  698.59   262.7  689.39
   270.7  685.35   281.6  681.48   298.6  680.17   302.5  681.27   310.5  687.64
   314.4  689.22  323.13 690.893   338.1  692.43  353.76692.8868   361.7  693.36
  384.38692.7881   401.1  692.18  415.01694.0668  445.64697.3362   448.4  697.69
#Mann= 8 ,-1 , 0
       0     .12       0   281.6    .045       0   302.5     .12       0
  323.13    .016       0  353.76     .08       0  384.38    .016       0
  415.01     .06       0  445.64     .08       0
Bank Sta=281.6,302.5
XS Rating Curve= 0 ,0
Exp/Cntr=0.3,0.1

Type RM Length L Ch R = 1 ,3302.2  ,439.4,415.9,391.9
XS GIS Cut Line= 2
     1688622.938      360686.232     1688688.699      361131.294
#Sta/Elev= 30
       0  742.78    23.9  736.05    43.8   730.8    51.8  729.09    55.7  727.64
    63.7  722.71    79.6  715.59    83.6  714.24    99.5  710.65   107.5  708.43
   119.4  702.84   127.4  700.06   131.4  698.06   155.3  680.39   159.2  677.97
   161.1   677.6   171.2  676.69   176.1  677.01   183.1   677.7   187.1  679.06
   195.1  683.86   199.1  685.27  204.82  685.81   274.7  686.66   298.6   686.6
   318.5  688.07   362.3  689.12   398.1  692.43     430  694.52   449.9  695.13
#Mann= 4 ,-1 , 0
       0     .12       0   161.1    .045       0   176.1     .12       0
  204.82     .08       0
Bank Sta=161.1,176.1
XS Rating Curve= 0 ,0
Exp/Cntr=0.3,0.1

Type RM Length L Ch R = 1 ,2886.2  ,496.5,511.1,524.9
XS GIS Cut Line= 4
     1688066.674      360912.958     1688077.392      360930.374
     1688532.449      361105.253     1688593.212      361289.715
#Sta/Elev= 30
       0  727.11    20.4  719.38    44.4  713.68   56.33709.7796   69.43706.9833
   87.98706.2352   124.3  705.09  151.26     705   220.2  703.05   224.2  701.82
   228.2  698.64   248.2  678.74   252.2  675.96   260.2  674.69   274.3  674.23
   280.2  673.71   284.2  673.76   289.3  675.06   300.2  681.08  309.46684.9684
   348.1  686.15     420  686.52  436.03687.1911  481.04689.0212   511.9  690.88
   551.6  691.66   658.6  695.74   682.4  695.87   698.2  699.56   702.2  700.01
#Mann= 10 ,-1 , 0
       0     .12       0   56.33     .06       0   69.43     .12       0
   87.98     .06       0  151.26     .12       0   274.3    .045       0
   289.3     .12       0  309.46     .08       0  436.03    .016       0
  481.04     .08       0
Bank Sta=274.3,289.3
XS Rating Curve= 0 ,0
Exp/Cntr=0.3,0.1

Type RM Length L Ch R = 1 ,2375.2  ,262.2,275.1,288
XS GIS Cut Line= 2
     1687914.444      361118.951     1688204.758      361567.492
#Sta/Elev= 30
       0  690.32     7.4  690.06   35.42689.1336   103.7  686.54  144.14  684.27
  148.12684.0352   179.4  682.26   198.5681.7372   219.3  682.06  252.86681.2236
  288.84679.7073  307.22678.7919  324.02677.3427   354.9   675.8   362.8  674.08
   371.7  669.65   374.8  669.15   386.7  670.13   402.7   674.9   418.7  681.75
  429.56687.1598   450.6  694.68   458.5  695.86  464.74696.0092   490.4   696.4
   498.4  695.92   510.4  693.82   514.4     694   526.3  696.16   534.3  696.61
#Mann= 14 ,-1 , 0
       0     .06       0     7.4     .08       0   35.42     .06       0
  144.14     .12       0  148.12     .06       0   198.5     .08       0
  252.86     .06       0  288.84     .08       0  307.22     .06       0
  324.02     .12       0   371.7    .045       0   386.7     .12       0
  429.56     .08       0  464.74    .016       0
Bank Sta=371.7,386.7
XS Rating Curve= 0 ,0
Exp/Cntr=0.3,0.1

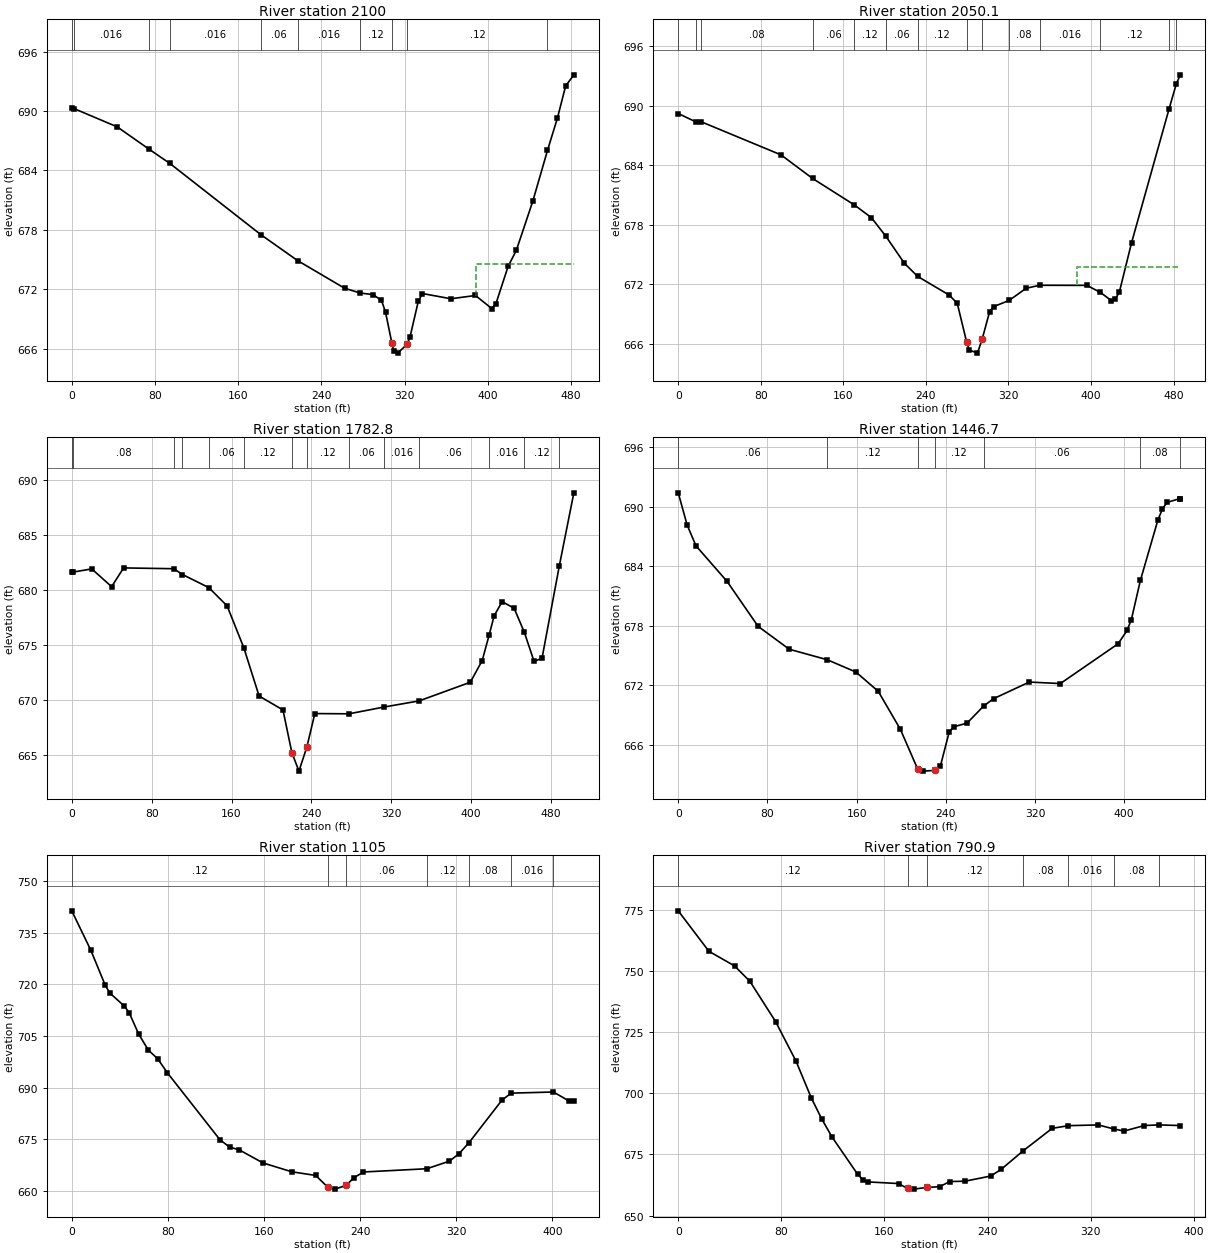
Type RM Length L Ch R = 1 ,2100    ,49.8,49.9,49.8
XS GIS Cut Line= 4
     1687795.353      361182.195     1687861.818      361415.675
     1687863.051      361608.254      1687887.38      361649.055
#Sta/Elev= 30
       0  690.29    2.12690.2423    43.8  688.39   73.79686.1786   94.24684.7103
  181.68677.5229  217.08674.8992   262.4   672.1  277.13671.6272   289.9  671.45
   297.8  670.87   301.7   669.7   307.7  666.62   309.6  665.77   313.5  665.55
   322.7  666.48   325.3   667.2   333.2  670.77   337.1  671.57   364.6  671.04
   388.2  671.37   403.9  670.05   407.8  670.52   419.6  674.31   427.5  675.93
   443.3  680.88  457.46686.0201     467  689.28   474.9  692.52   482.8  693.65
#Mann= 10 ,-1 , 0
       0     .08       0    2.12    .016       0   73.79     .06       0
   94.24    .016       0  181.68     .06       0  217.08    .016       0
  277.13     .12       0   307.7    .045       0   322.7     .12       0
  457.46     .08       0
#XS Ineff= 2 , 0
                          389.04          674.57
Permanent Ineff=
       F       F
Bank Sta=307.7,322.7
XS Rating Curve= 0 ,0
Exp/Cntr=0.3,0.1

Type RM Length L Ch R = 1 ,2050.1  ,279.6,267.3,254.2
XS GIS Cut Line= 4
     1687750.379      361197.354     1687813.641      361419.582
     1687814.874       361612.16     1687847.136      361666.266
#Sta/Elev= 30
       0  689.21   17.07688.3658    22.3 688.374    99.6  685.04  130.19682.6613
  170.61679.9966   187.2  678.71  201.32676.8208   219.1  674.12  231.99672.7898
   262.5  670.91   270.4  670.08   279.6  666.13   282.2  665.36     290  665.05
   294.6  666.47   301.8  669.24   305.7  669.74  320.59670.3564   337.2  671.59
  350.13671.8903   396.1  671.88   409.2671.1667   419.7  670.35   423.6  670.49
   427.6  671.24   439.4   676.2   475.6 689.636  482.67692.1801   486.6  693.11
#Mann= 14 ,-1 , 0
       0     .08       0   17.07     .12       0    22.3     .08       0
  130.19     .06       0  170.61     .12       0  201.32     .06       0
  231.99     .12       0   279.6    .045       0   294.6     .12       0
  320.59     .08       0  350.13    .016       0   409.2     .12       0
   475.6     .08       0  482.67    .016       0
#XS Ineff= 2 , 0
                          386.94          673.76
Permanent Ineff=
       F       F
Bank Sta=279.6,294.6
XS Rating Curve= 0 ,0
Exp/Cntr=0.3,0.1

Type RM Length L Ch R = 1 ,1782.8  ,335.6,336.1,335.7
XS GIS Cut Line= 2
     1687430.747      361305.096     1687702.617      361728.073
#Sta/Elev= 30
       0  681.67    1.59681.6262      20  681.91    39.9   680.3    51.9     682
  102.11681.9272  110.85681.4014  137.22680.2156   155.6  678.55  172.33674.7481
   187.6  670.38   211.5  669.12   220.4  665.25   227.5  663.57   235.4  665.75
   243.4  668.79  277.65668.7685  312.76669.3839  347.87669.9401   399.1  671.63
     411  673.59  418.08675.9511     423  677.66     431  678.94     443  678.34
  453.19676.1672   462.9  673.54   470.9  673.79   488.3682.2112   502.8  688.81
#Mann= 14 ,-1 , 0
       0     .06       0    1.59     .08       0  102.11     .06       0
  110.85     .08       0  137.22     .06       0  172.33     .12       0
   220.4    .045       0   235.4     .12       0  277.65     .06       0
  312.76    .016       0  347.87     .06       0  418.08    .016       0
  453.19     .12       0   488.3     .08       0
Bank Sta=220.4,235.4
XS Rating Curve= 0 ,0
Exp/Cntr=0.3,0.1

Type RM Length L Ch R = 1 ,1446.7  ,340.9,341.7,341.2
XS GIS Cut Line= 2
     1687185.906      361514.806     1687429.422      361893.669
#Sta/Elev= 30
       0  691.38       8  688.13    15.9  686.04    43.8  682.45    71.7  677.91
    99.6  675.61   133.7674.5495   159.4  673.31   179.4  671.37   199.3  667.53
   214.9   663.5   219.2  663.32   229.9  663.39   235.2  663.84   243.1  667.28
   247.1  667.79   259.1  668.16  274.14669.9033     283  670.63   314.9   672.3
   342.8  672.15   394.6  676.16   402.6   677.5   406.5   678.6  414.57682.5452
   430.4  688.68   434.4  689.76   438.4  690.41  449.68690.7874   450.4   690.8
#Mann= 7 ,-1 , 0
       0     .06       0   133.7     .12       0   214.9    .045       0
   229.9     .12       0  274.14     .06       0  414.57     .08       0
  449.68    .016       0
Bank Sta=214.9,229.9
XS Rating Curve= 0 ,0
Exp/Cntr=0.3,0.1

Type RM Length L Ch R = 1 ,1105    ,314.8,314.1,313.5
XS GIS Cut Line= 2
     1686931.276       361733.06     1687157.226      362084.593
#Sta/Elev= 30
       0   741.3    15.9  729.84    27.9  719.68    31.8  717.42    43.8  713.66
    47.8  711.74    55.7  705.55    63.7  700.93    71.6  698.36    79.6  694.32
   123.4  674.89   131.3   672.8   139.3     672   159.2  668.19   183.1  665.63
     203  664.57   213.3   661.1   218.9   660.6   228.3  661.66   234.8   663.9
   242.8  665.57  295.57666.5129   314.4  668.72   322.4   670.9  330.68674.0882
   358.2  686.47  365.79688.4341   400.9688.7635   413.9  686.16   417.9  686.22
#Mann= 7 ,-1 , 0
       0     .12       0   213.3    .045       0   228.3     .06       0
  295.57     .12       0  330.68     .08       0  365.79    .016       0
   400.9     .08       0
Bank Sta=213.3,228.3
XS Rating Curve= 0 ,0
Exp/Cntr=0.3,0.1

Type RM Length L Ch R = 1 ,790.9   ,359.2,359.4,358.5
XS GIS Cut Line= 2
     1686694.573      361933.775     1686905.156      362261.401
#Sta/Elev= 30
       0  774.53    23.8     758    43.7  752.02    55.6  745.72    75.5  729.31
    91.4  713.09   103.3  698.01   111.3  689.52   119.2  682.21   139.1  666.95
   143.1  664.74     147  663.78   170.9  663.11   177.9  661.09   182.8  660.83
   192.9  661.54   202.7   661.8   210.6  663.92   222.6  664.08   242.4  666.18
   250.4  668.85  267.64676.5063   290.1  685.66  302.75686.7606   325.9  687.06
  337.86685.4195   345.8  684.54   361.6  686.81  372.97687.0695   389.5   686.8
#Mann= 7 ,-1 , 0
       0     .12       0   177.9    .045       0   192.9     .12       0
  267.64     .08       0  302.75    .016       0  337.86     .08       0
  372.97    .016       0
Bank Sta=177.9,192.9
XS Rating Curve= 0 ,0
Exp/Cntr=0.3,0.1

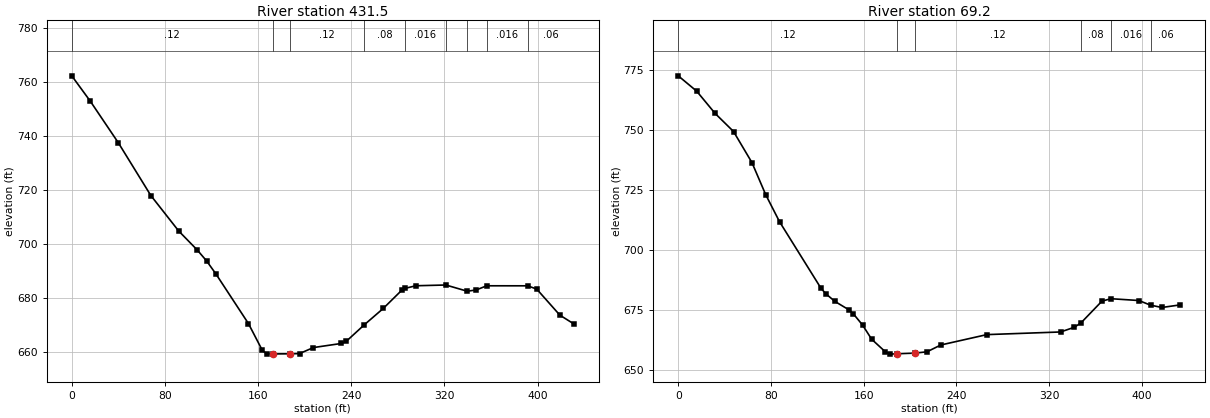
Type RM Length L Ch R = 1 ,431.5   ,346,362.4,378.2
XS GIS Cut Line= 2
     1686391.495      362095.417     1686624.647      362458.156
#Sta/Elev= 30
       0  762.32      16  752.86    39.9  737.56    67.9  717.95    91.8  704.81
   107.8  697.73   115.8  693.69   123.8  688.87   151.7  670.49   163.7   660.5
   167.7  659.14   172.8  659.22   187.8  659.26   195.6  659.35   207.6  661.58
   231.6   663.1   235.6  663.83  251.05669.9449   267.5  676.07   283.5  682.87
  286.16683.5151   295.5  684.49  321.27684.7679  339.67682.4601   347.4  682.94
  356.38 684.478  391.49684.4672   399.3  683.26   419.2  673.59   431.2  670.34
#Mann= 9 ,-1 , 0
       0     .12       0   172.8    .045       0   187.8     .12       0
  251.05     .08       0  286.16    .016       0  321.27     .06       0
  339.67     .08       0  356.38    .016       0  391.49     .06       0
Bank Sta=172.8,187.8
XS Rating Curve= 0 ,0
Exp/Cntr=0.3,0.1

Type RM Length L Ch R = 1 ,69.2    ,75.3,69.2,63.3
XS GIS Cut Line= 2
     1686192.678      362111.281     1686122.444      362538.737
#Sta/Elev= 30
       0  772.55    15.9  766.17    31.8   756.9    47.7  749.36    63.6  736.41
    75.5  723.02    87.4  711.78   123.2  684.04   127.2  681.84   135.1  678.61
     147  675.16     151  673.47     159  668.77   166.9  662.83   178.8  657.55
   182.8  656.63     189  656.79     204  657.05   214.6  657.59   226.5  660.43
   266.3  664.76   329.9  665.86   341.8  667.83  347.62 669.702   365.6  678.71
   373.4679.7125   397.4  678.96  407.48 677.036   417.3  676.06   433.2  677.15
#Mann= 6 ,-1 , 0
       0     .12       0     189    .045       0     204     .12       0
  347.62     .08       0   373.4    .016       0  407.48     .06       0
Bank Sta=189,204
XS Rating Curve= 0 ,0
Exp/Cntr=0.3,0.1

Chan Stop Cuts=-1
Use User Specified Reach Order=0
Composite Channel Slope=5